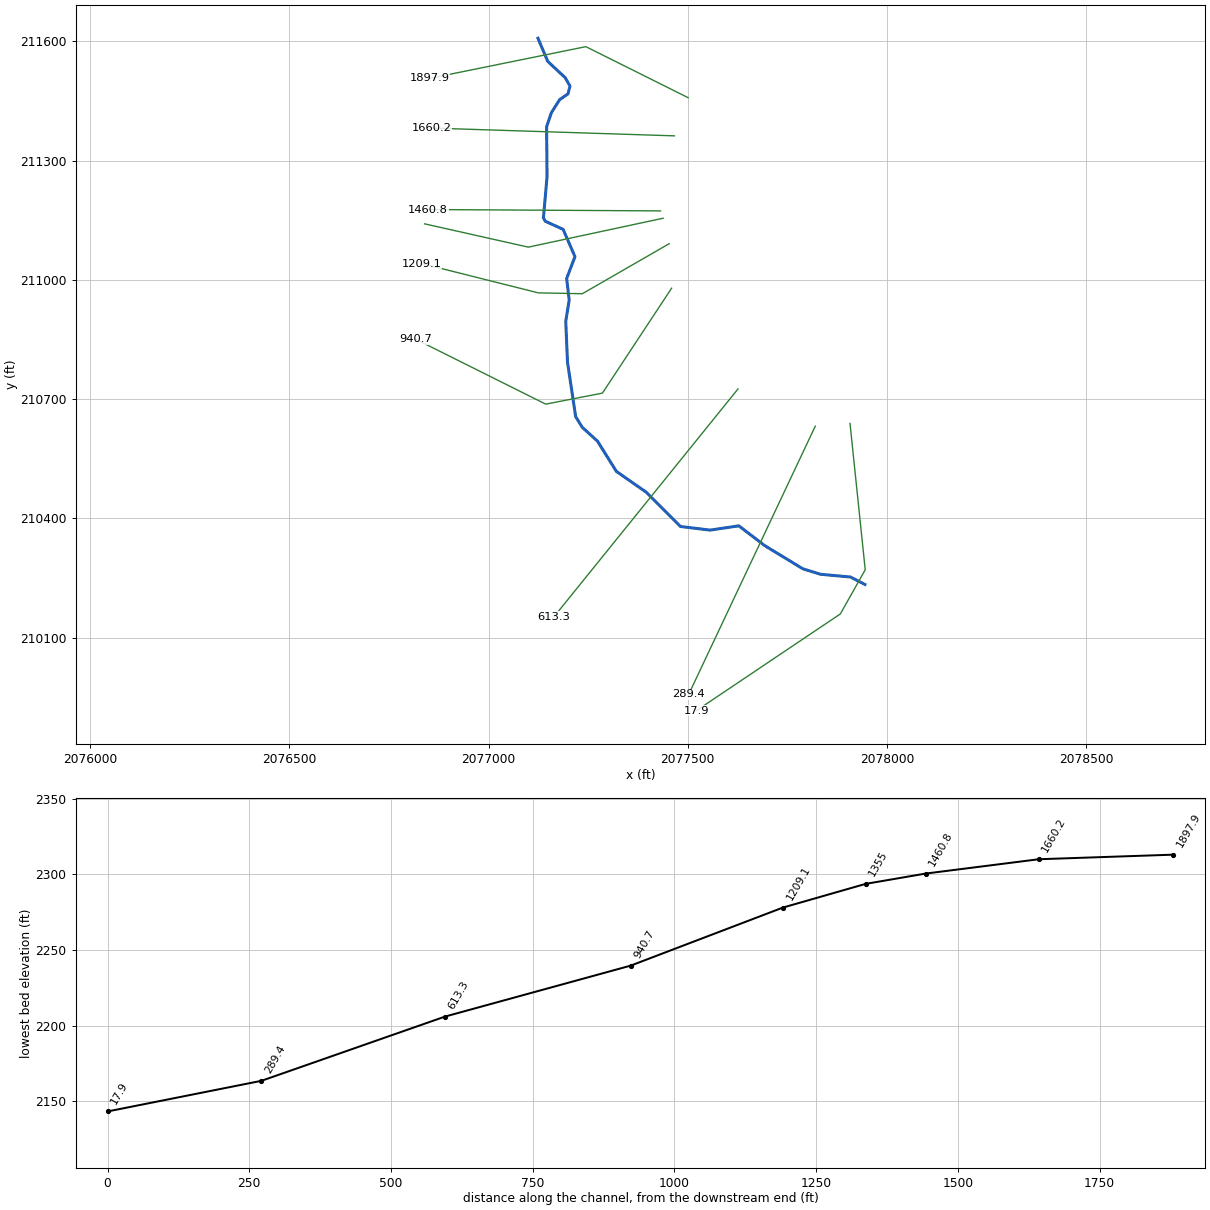
--- SRTNBRCH.prj (project) ---

Proj Title=SRTNBRCH
Current Plan=p01
Default Exp/Contr=0,0
English Units
Geom File=g01
Flow File=f01
Plan File=p01
BEGIN DESCRIPTION:
END DESCRIPTION:
DSS Export Rating Curves= 0
DSS Export Rating Curve Sorted= 0
DSS Export Volume Flow Curves= 0
DXF OffsetX= 0
DXF OffsetY= 0
DXF ScaleX= 0
DXF ScaleY= 0

--- SRTNBRCH.p01 (plan) ---

Plan Title=Floodplain
Program Version=4.00
Geom File=g01
Flow File=f01
K Sum by GR=0
Std Step Tol=0.01
Critical Tol=0.01
Num of Std Step Trials=20
Max Error Tol=0.3
Flow Tol Ratio=0.001
Split Flow NTrial=30
Split Flow Tol=0.02
Split Flow Ratio=0.02
Log Output Level=0
Friction Slope Method=1
Unsteady Friction Slope Method=2
Unsteady Bridges Friction Slope Method=1
Global Log Level=0
CheckData=False
Run HTab=0
Run UNet=0
Run PostProcess=0
UNET Theta=0
UNET Theta Warmup=0
UNET ZTol=0
UNET ZSATol=0
UNET MxIter=0
UNET MaxInSteps=0
UNET DtIC=0
UNET DtMin=0
UNET MaxCRTS=0
UNET WFStab=0
UNET SFStab=0
UNET WFX=0
UNET SFX=0
UNET DSS MLevel=0
UNET DZMax Abort=0
UNET Convert EG Bridges=0
UNET Use Existing IB Tables=0
UNET Froude Limit=0
UNET Froude Power=0
Write IC File=0
Echo Input=False
Echo Output=False
Write Detailed=0

--- SRTNBRCH.f01 (steady flow) ---

Flow Title=2010 USGS WV Regression Equation
Program Version=4.10
Number of Profiles= 1
Profile Names=P100yr
River Rch & RM=SRTNBRCH,Main            ,1897.9
573.5116
River Rch & RM=SRTNBRCH,Main            ,289.4
598.8227
River Rch & RM=SRTNBRCH,Main            ,289.4
596.5329
Boundary for River Rch & Prof#=SRTNBRCH,Main            , 1
Up Type= 0
Dn Type= 3
Dn Slope=0.0738
DSS Import GetInterval= 0
DSS Import GetPeak= 0
DSS Import FillOption= 0

--- SRTNBRCH.g01 (geometry) ---

Geom Title=LiDAR
Program Version=4.10

River Reach=SRTNBRCH        ,Main
Reach XY= 30
     2077123.778      211608.141     2077148.337      211549.969
     2077192.607      211508.303     2077204.326      211487.469
     2077199.118      211467.938     2077178.285      211453.615
      2077157.69       211421.02     2077145.537      211385.429
     2077146.601      211259.605     2077137.573      211155.959
      2077142.26      211147.626     2077187.052      211127.313
      2077216.74      211058.563     2077195.906      211003.876
     2077202.187      210949.321     2077193.581      210895.748
     2077197.989      210793.459     2077218.454      210656.263
     2077234.947      210629.353     2077273.141      210594.631
     2077320.884      210518.242     2077395.537      210466.159
     2077481.584      210379.835      2077555.78      210370.716
       2077628.1      210381.458     2077693.161      210331.675
     2077788.647      210273.516     2077832.918      210259.626
     2077908.439      210252.682     2077944.858      210233.888

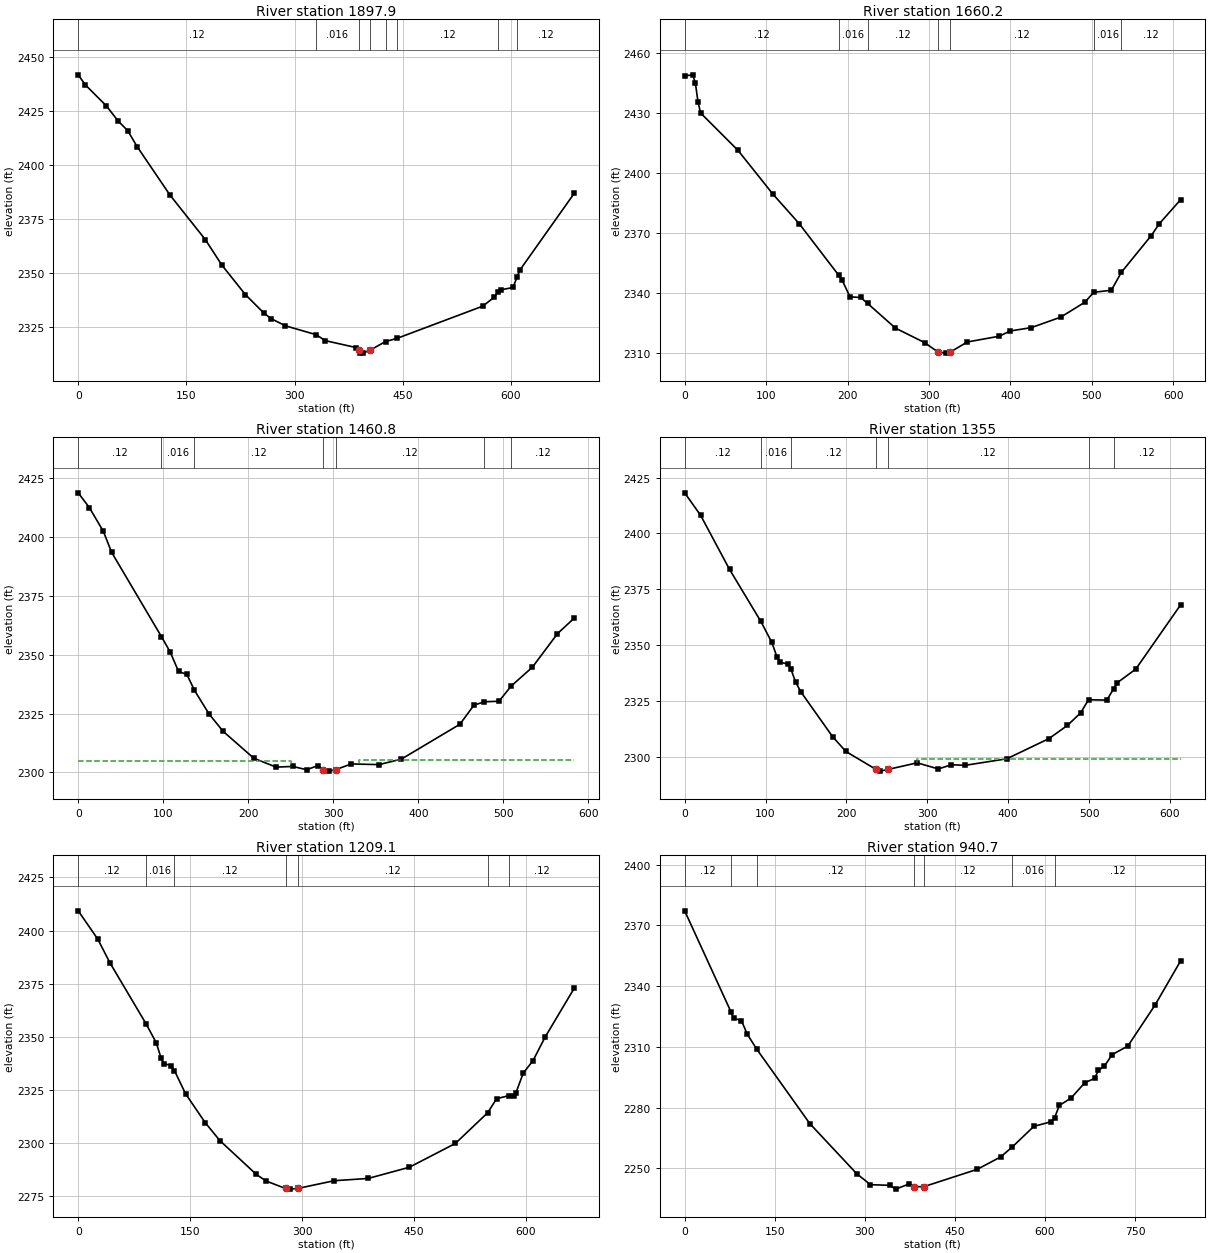
Type RM Length L Ch R = 1 ,1897.9  ,243.2,237.6,230.6
XS GIS Cut Line= 3
     2077501.007       211458.42     2077244.062      211586.892
     2076851.701      211507.031
#Sta/Elev= 30
       0 2441.77     9.8 2437.16    39.2 2427.36    55.5 2420.35    68.6 2415.98
    81.6 2408.61   127.3 2386.13   176.3 2365.54   199.1  2353.8   231.8 2340.12
   257.9 2331.42   267.7 2328.97   287.3 2325.68  330.022321.559   342.6 2318.82
   384.9 2315.64  388.942314.369   391.4 2313.27   394.7 2313.04   404.5 2314.37
  426.122318.388   442.32319.895   560.7 2334.74     577  2338.9   581.92341.187
   586.8 2342.38     603  2343.4  608.562348.312   612.8 2351.62   687.7  2386.9
#Mann= 8 ,-1 , 0
       0     .12       0  330.02    .016       0  388.94    .045       0
   404.5     .12       0  426.12     .06       0   442.3     .12       0
   581.9    .016       0  608.56     .12       0
Bank Sta=388.94,404.5
XS Rating Curve= 0 ,0
Exp/Cntr=0.3,0.1

Type RM Length L Ch R = 1 ,1660.2  ,198.5,199.5,199.7
XS GIS Cut Line= 2
     2077466.357        211362.5     2076857.633      211382.031
#Sta/Elev= 30
       0 2448.61     9.8 2449.13    13.1 2445.19    16.4 2435.45    19.6 2430.04
    65.5 2411.36     108 2389.66   140.8 2374.64  189.112348.952   193.2 2346.61
     203 2338.15   216.1 2337.82  224.522334.904   258.7 2322.54   294.7 2315.25
   311.1 2310.56   320.9 2310.01  326.152310.548   347.1 2315.58   386.4 2318.47
   399.5 2321.06   425.7 2322.77   461.7 2327.98   491.2  2335.4  502.342340.428
   523.9 2341.44  536.362350.467     573  2368.8   582.8 2374.68     609 2386.71
#Mann= 7 ,-1 , 0
       0     .12       0  189.11    .016       0  224.52     .12       0
   311.1    .045       0  326.15     .12       0  502.34    .016       0
  536.36     .12       0
Bank Sta=311.1,326.15
XS Rating Curve= 0 ,0
Exp/Cntr=0.3,0.1

Type RM Length L Ch R = 1 ,1460.8  ,99.5,105.8,110.7
XS GIS Cut Line= 2
     2077431.562      211173.698     2076848.229       211177.17
#Sta/Elev= 30
       0 2418.84    13.1 2412.56    29.5 2402.51    39.3 2393.54   97.792357.762
   108.2 2351.16     118  2342.9   127.8 2341.66  136.752334.851     154 2324.77
   170.4 2317.46   206.5 2306.01   232.7 2302.24   252.4 2302.52   268.7 2301.12
   281.8 2302.86   288.4 2301.18     295 2300.53  303.022301.183   321.2 2303.58
   353.9  2303.3   380.2 2305.66     449 2320.47   465.4 2328.57  477.67 2330.01
   494.9 2330.24  509.332336.737   534.2 2344.71   563.7 2358.98   583.3 2365.54
#Mann= 7 ,-1 , 0
       0     .12       0   97.79    .016       0  136.75     .12       0
   288.4    .045       0  303.02     .12       0  477.67    .016       0
  509.33     .12       0
#XS Ineff= 2 , 0
          250.43 2304.84  330.12         2305.06
Permanent Ineff=
       F       F
Bank Sta=288.4,303.02
XS Rating Curve= 0 ,0
Exp/Cntr=0.3,0.1

Type RM Length L Ch R = 1 ,1355    ,151.1,145.9,139.7
XS GIS Cut Line= 3
     2077438.145      211155.251     2077099.604      211082.552
     2076839.187      211141.145
#Sta/Elev= 30
       0 2418.17    19.6 2408.17    55.5  2383.9   94.182360.659   107.8 2351.24
   114.3 2344.61   117.6 2342.43   127.4 2341.63  131.432339.271   137.2 2333.51
   143.7 2329.14   182.9 2309.13   199.3 2302.51  236.322294.548   241.7 2293.72
   251.5 2294.49   287.5 2297.43   313.6 2294.69   329.9 2296.59   346.3 2296.29
   398.3 2299.24   450.4 2308.26   473.2 2314.15   489.5 2319.75   499.3 2325.63
     522 2325.48  530.242330.475   535.1  2333.3   557.8 2339.37   613.2 2368.07
#Mann= 7 ,-1 , 0
       0     .12       0   94.18    .016       0  131.43     .12       0
  236.32    .045       0   251.5     .12       0   499.3    .016       0
  530.24     .12       0
#XS Ineff= 2 , 0
                          286.73         2298.92
Permanent Ineff=
       F       F
Bank Sta=236.32,251.5
XS Rating Curve= 0 ,0
Exp/Cntr=0.3,0.1

Type RM Length L Ch R = 1 ,1209.1  ,262.5,268.5,272.1
XS GIS Cut Line= 4
     2077453.336      211091.232     2077235.237      210965.364
      2077124.56      210967.534     2076831.591      211041.319
#Sta/Elev= 30
       0 2409.28    26.2 2395.94    42.5 2384.77   91.042355.936   104.6 2347.06
   111.2 2339.68   114.5 2337.28   124.3 2336.32  129.012333.927   143.9 2322.99
   170.1 2309.46   189.7 2300.98   238.7 2284.99   251.8 2281.89   277.9 2278.36
   284.4 2278.06   294.1 2278.37     343 2282.03   388.5 2283.09   443.7 2288.37
   505.4 2299.59  548.552314.023   560.7  2320.7  577.552322.166   583.4 2322.02
   586.7  2323.6   596.4 2332.79   609.4  2338.6   625.6 2349.69   664.6 2372.73
#Mann= 7 ,-1 , 0
       0     .12       0   91.04    .016       0  129.01     .12       0
   277.9    .045       0   294.1     .12       0  548.55    .016       0
  577.55     .12       0
Bank Sta=277.9,294.1
XS Rating Curve= 0 ,0
Exp/Cntr=0.3,0.1

Type RM Length L Ch R = 1 ,940.7   ,310.3,327.3,342.2
XS GIS Cut Line= 4
      2077459.34      210979.253     2077285.729      210715.364
     2077143.368      210687.586     2076816.979      210850.781
#Sta/Elev= 30
       0 2377.17   76.842327.413    81.4 2324.12    94.4 2322.96   104.2 2316.24
  119.832308.889   208.4 2272.04   286.6 2247.25   309.4 2241.88   341.7 2241.55
   351.3 2239.68   373.9 2242.25  382.052240.905   398.1 2240.88     487 2249.45
   526.1 2255.57  545.652260.546   581.5 2270.71   610.8 2273.01     6162274.937
   623.8 2281.01   643.4 2284.68   666.2 2292.23   682.5 2294.38     689  2298.4
   698.8 2300.38   711.8 2306.15   737.9 2310.35   783.5 2330.76   825.8 2352.44
#Mann= 7 ,-1 , 0
       0     .12       0   76.84    .016       0  119.83     .12       0
  382.05    .045       0   398.1     .12       0  545.65    .016       0
     616     .12       0
Bank Sta=382.05,398.1
XS Rating Curve= 0 ,0
Exp/Cntr=0.3,0.1

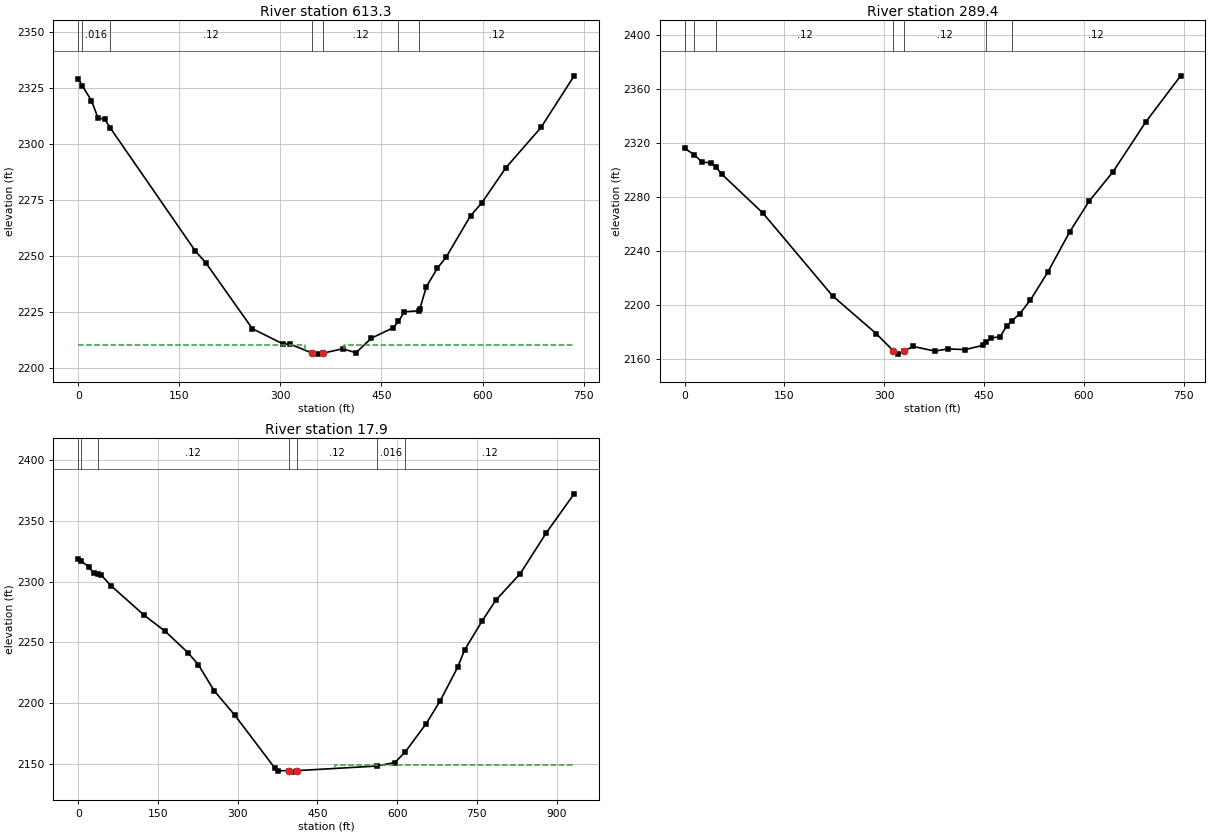
Type RM Length L Ch R = 1 ,613.3   ,317.2,323.9,326.6
XS GIS Cut Line= 2
     2077626.007      210725.781     2077164.201      210152.864
#Sta/Elev= 30
       0 2329.11    5.982325.993    19.6 2319.34    29.4 2311.55    39.2 2311.01
   47.412307.189   173.3 2252.31   189.7 2246.68   258.4 2217.39   304.2 2210.53
     314 2210.54   346.7 2206.53   356.5 2206.02     363 2206.43   392.5 2208.41
   412.1 2206.63     435 2213.13   467.7 2217.85  475.092220.631     484 2224.94
  505.162225.387   506.9 2226.29   516.7 2236.23   533.1 2244.47   546.2 2249.49
   582.2 2267.88   598.5 2273.47   634.5 2289.28   686.8 2307.34   735.9 2330.39
#Mann= 7 ,-1 , 0
       0     .12       0    5.98    .016       0   47.41     .12       0
   346.7    .045       0     363     .12       0  475.09    .016       0
  505.16     .12       0
#XS Ineff= 2 , 0
          336.81 2209.95   393.9         2210.28
Permanent Ineff=
       F       F
Bank Sta=346.7,363
XS Rating Curve= 0 ,0
Exp/Cntr=0.3,0.1

Type RM Length L Ch R = 1 ,289.4   ,273.1,271.5,269.3
XS GIS Cut Line= 2
      2077820.09      210632.248     2077502.381      209957.769
#Sta/Elev= 30
       0 2316.03   14.222311.462    26.2 2305.83    39.2 2305.34   46.822302.394
    55.6 2297.02   117.7 2268.03   222.4 2206.69   287.8 2178.81   313.9 2165.89
   320.5 2163.54   330.1  2165.8   343.4 2169.24     376 2165.81   395.7 2167.39
   421.8  2166.9     448 2170.02  453.512172.616   461.1  2175.6   474.2 2176.33
     484 2184.39  491.752188.096   503.6 2193.36   519.9 2203.75   546.1 2224.47
   578.8 2254.12   608.2 2276.99   644.2 2298.84   693.2 2335.64   745.6 2369.82
#Mann= 7 ,-1 , 0
       0     .12       0   14.22    .016       0   46.82     .12       0
   313.9    .045       0   330.1     .12       0  453.51    .016       0
  491.75     .12       0
Bank Sta=313.9,330.1
XS Rating Curve= 0 ,0
Exp/Cntr=0.3,0.1

Type RM Length L Ch R = 1 ,17.9    ,13.7,17.9,22.2
XS GIS Cut Line= 4
     2077907.257      210638.975     2077945.451       210270.92
     2077882.951      210159.809      2077521.84      209916.753
#Sta/Elev= 30
       0 2318.49    5.692316.804    19.6  2312.4    29.5 2306.82   36.692306.433
    42.6 2305.73    62.2 2296.47   124.4 2272.28   163.7 2259.15   206.3 2241.62
     226 2231.66   255.4 2210.44   294.7 2190.02     370 2146.52   376.6 2144.42
   396.2 2144.56   402.7 2143.28  411.46 2144.51  561.372148.292   595.7  2151.2
  615.172159.925   654.6 2183.24   680.8 2201.92   713.5  2229.4   726.6 2243.71
   759.3  2267.4   785.5 2284.79   831.4 2306.63   880.4 2340.24   932.8 2372.31
#Mann= 7 ,-1 , 0
       0     .12       0    5.69    .016       0   36.69     .12       0
   396.2    .045       0  411.46     .12       0  561.37    .016       0
  615.17     .12       0
#XS Ineff= 2 , 0
                          482.51         2149.41
Permanent Ineff=
       F       F
Bank Sta=396.2,411.46
XS Rating Curve= 0 ,0
Exp/Cntr=0.3,0.1

Chan Stop Cuts=-1
Use User Specified Reach Order=0
Composite Channel Slope=5